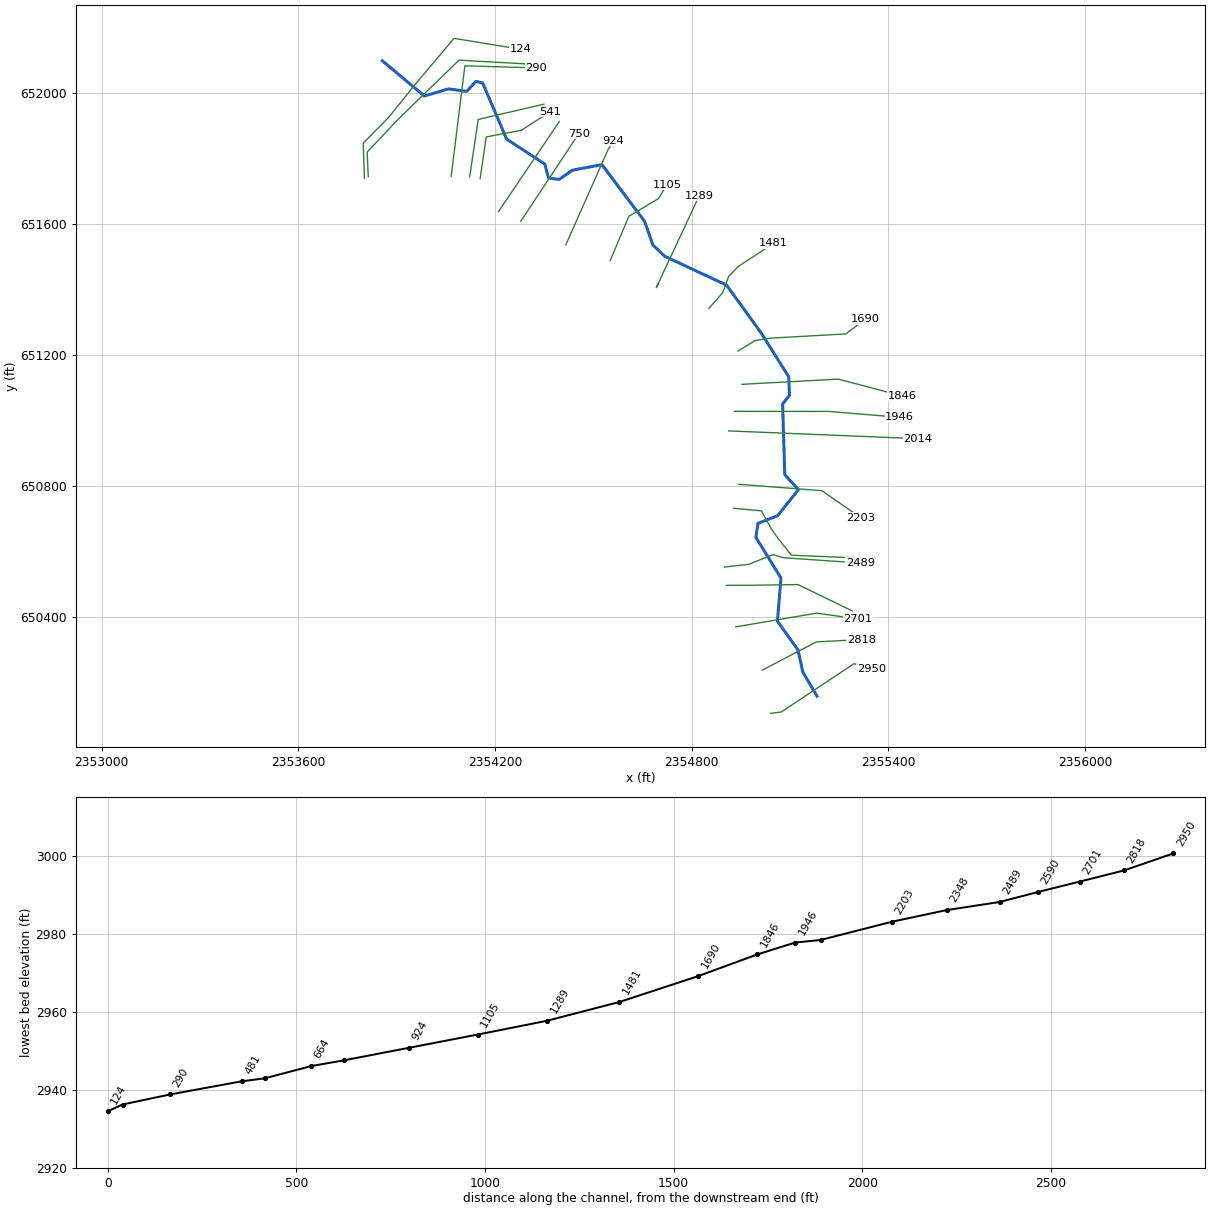
--- LAURELFKT4.prj (project) ---

Proj Title=LAURELFKT4
Current Plan=p01
Default Exp/Contr=0,0
English Units
Geom File=g01
Flow File=f01
Plan File=p01
Background Map Layer=Inundation Boundary (P100yr Value_0)
BEGIN DESCRIPTION:
----------MODEL BY WOOD PLC 2022----------
AFH study
Randolph County, WV
HEC-RAS Version: RAS 6.2
Vertical Datum: NAVD88
Projection: NAD 1983 StatePlane West Virginia S FIPS 4702 (US Feet)
Terrain: 1-meter LIDAR (FEMA Region III 3DEP collected 2016-2018)
Land Use: 2019 NLCD
Hydrologic Method:
WV SIR2010-5033 regression equations
Additional Model Notes:
None
END DESCRIPTION:
DSS Export Rating Curves= 0
DSS Export Rating Curve Sorted= 0
DSS Export Volume Flow Curves= 0
DXF OffsetX= 0
DXF OffsetY= 0
DXF ScaleX= 0
DXF ScaleY= 0

--- LAURELFKT4.p01 (plan) ---

Plan Title=Floodplain
Program Version=4.00
Geom File=g01
Flow File=f01
K Sum by GR=0
Std Step Tol=0.01
Critical Tol=0.01
Num of Std Step Trials=20
Max Error Tol=0.3
Flow Tol Ratio=0.001
Split Flow NTrial=30
Split Flow Tol=0.02
Split Flow Ratio=0.02
Log Output Level=0
Friction Slope Method=1
Unsteady Friction Slope Method=2
Unsteady Bridges Friction Slope Method=1
Global Log Level=0
CheckData=False
Run HTab=0
Run UNet=0
Run PostProcess=0
UNET Theta=0
UNET Theta Warmup=0
UNET ZTol=0
UNET ZSATol=0
UNET MxIter=0
UNET MaxInSteps=0
UNET DtIC=0
UNET DtMin=0
UNET MaxCRTS=0
UNET WFStab=0
UNET SFStab=0
UNET WFX=0
UNET SFX=0
UNET DSS MLevel=0
UNET DZMax Abort=0
UNET Convert EG Bridges=0
UNET Use Existing IB Tables=0
UNET Froude Limit=0
UNET Froude Power=0
Write IC File=0
Echo Input=False
Echo Output=False
Write Detailed=0

--- LAURELFKT4.f01 (steady flow) ---

Flow Title=Flow
Program Version=4.00
Number of Profiles=1
Profile Names=P100yr
River Rch & RM=LAURELFKT4,Main,2950
     360
River Rch & RM=LAURELFKT4,Main,2014
     403
Boundary for River Rch & Prof#=LAURELFKT4,Main      ,1
Up Type=0
Dn Type=3
Dn Slope=0.025164

--- LAURELFKT4.g01 (geometry) ---

Geom Title=Geometry
Program Version=6.20

River Reach=LAURELFKT4      ,Main
Reach XY= 30
2355182.79152262650158.7456532792355139.43700001650232.548999995
2355124.76300003650299.9000000062355061.95800003650387.364999995
     2355072.809650518.8760000172354996.09759156650643.555828967
2355002.78786021650685.8855422892355062.85804168650709.487979173
2355125.99204745650788.8447481792355084.39450365650834.414000005
2355077.84911926651050.2053885692355098.86982401651076.936242628
2355096.46441576 651133.183558382355012.56094961651266.791888294
2354906.67571804 651412.974890972354717.73309508 651501.19555308
2354681.81972742651535.6213059322354656.57600002651607.850999996
2354526.50921311651780.513703516     2354436.458651763.622000009
2354395.98800002651735.3690000182354363.57857496651739.648515497
2354352.11742525651782.2907342522354235.65599999651858.371999994
     2354162.402652029.9309999942354141.49700004652034.144000009
2354114.11942501 652004.102160412354058.13900001652011.584000006
     2353984.788651989.8830000162353856.62470628652097.303094217

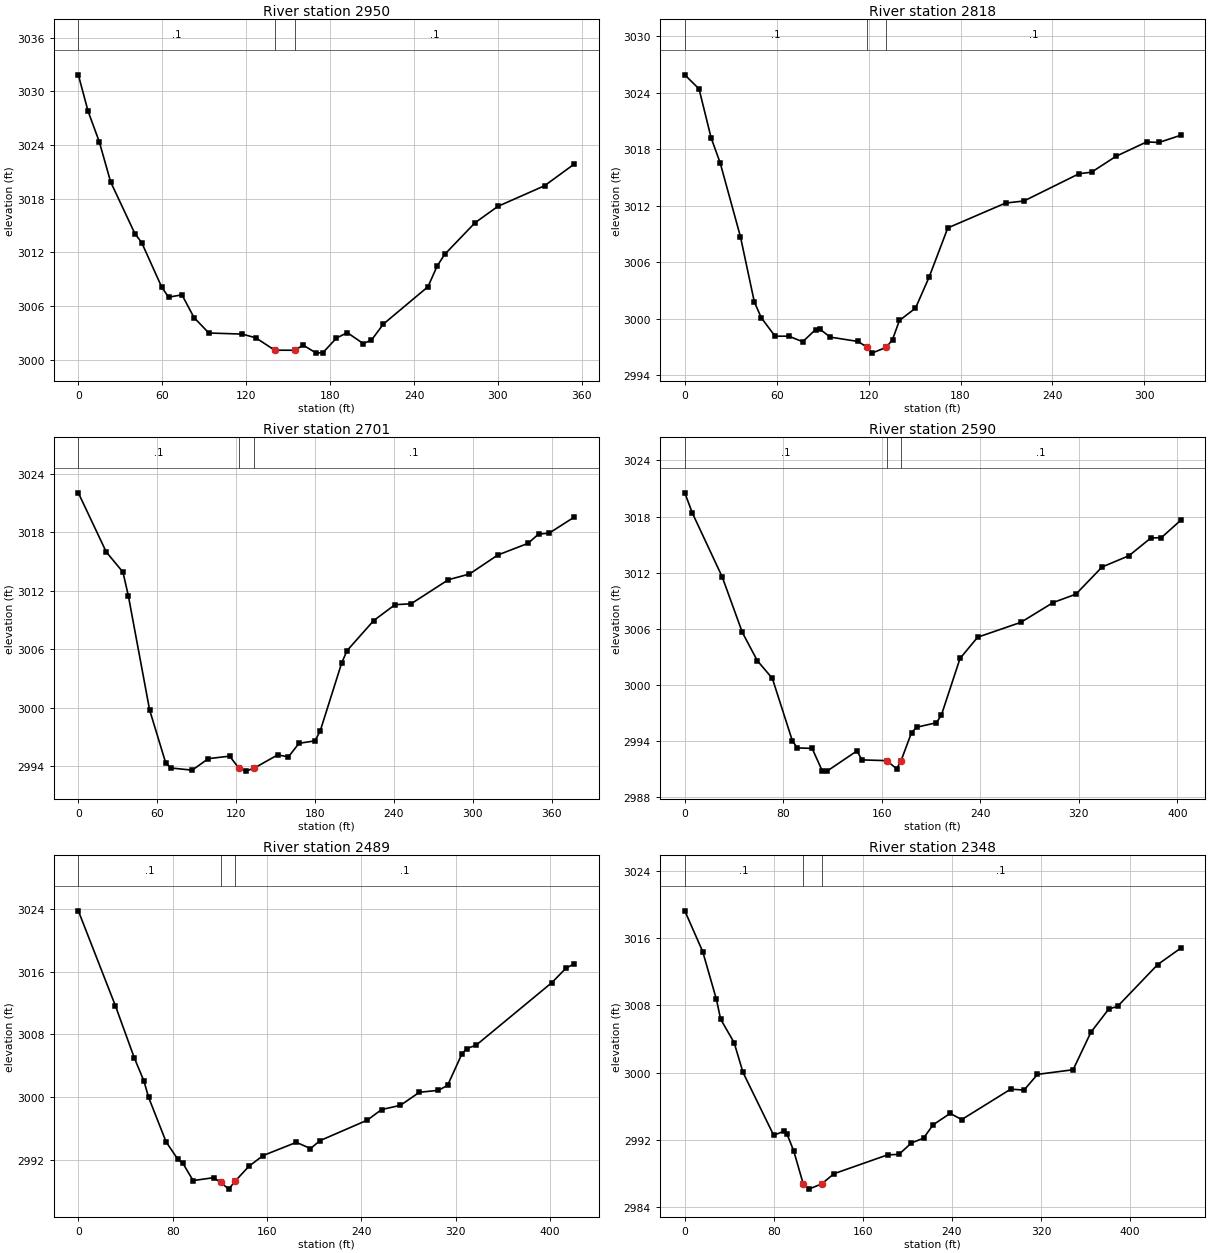
Type RM Length L Ch R = 1 ,2950    ,132.2,131.3,130.5
XS GIS Cut Line= 4
  2355041.279526650106.1573118532355073.81907855650110.438831926
2355295.70098351650257.7905722652355348.44525571650240.972749171
#Sta/Elev= 30
       0 3031.85       7 3027.76      15 3024.35    23.1 3019.87    40.4  3014.1
    45.3 3013.08    59.6 3008.11    64.5 3006.98    74.1 3007.24    82.7  3004.7
    93.3 3002.97   117.2 3002.85   126.9 3002.43   140.4 3001.05  154.85 3001.04
   160.7 3001.62   170.1 3000.72     175 3000.79   184.5  3002.4   192.3 3003.01
   203.7 3001.79   209.6 3002.18   218.1 3003.97     250 3008.15   256.5 3010.45
   261.9 3011.76   283.6  3015.3     300 3017.14   333.3 3019.44   354.5 3021.86
#Mann= 3 ,-1,0
       0      .1       0   140.4    .045       0  154.85      .1       0
Bank Sta=140.4,154.85
XS Rating Curve= 0 ,0
Exp/Cntr(USF)=0,0
Exp/Cntr=0.3,0.1

Type RM Length L Ch R = 1 ,2818    ,118.6,116.9,115.1
XS GIS Cut Line= 3
2355015.96543438  650238.21343432355180.84844079650324.352841344
2355318.32345405650331.313601509
#Sta/Elev= 30
       0 3025.91     9.3 3024.41    17.2  3019.2    23.1 3016.55    36.3 3008.72
    45.4 3001.77    49.9  3000.1    58.9 2998.13    67.9 2998.13      77 2997.54
    85.4 2998.84    88.3 2998.86      95 2998.03   113.1 2997.57  119.12 2996.94
   122.1 2996.33   131.6 2996.95   135.6 2997.77   140.1  2999.8   150.6 3001.11
   159.5 3004.41   171.7 3009.64   209.4 3012.28   221.4  3012.5   257.4  3015.4
   265.5 3015.56   281.5 3017.25   301.5 3018.78   309.5 3018.72323.6791 3019.48
#Mann= 3 ,-1,0
       0      .1       0  119.12    .045       0   131.6      .1       0
Bank Sta=119.12,131.6
XS Rating Curve= 0 ,0
Exp/Cntr(USF)=0,0
Exp/Cntr=0.3,0.1

Type RM Length L Ch R = 1 ,2701    ,112.3,111.5,110.5
XS GIS Cut Line= 3
2354934.74547022 650370.148235512355181.80948843650412.041699467
2355306.95278461650394.317541639
#Sta/Elev= 30
       0 3022.07    21.2    3016    33.9 3013.93      38 3011.51    54.2 2999.76
    66.4 2994.34    70.4  2993.8    86.6 2993.58    98.8 2994.76     115 2995.02
  122.08 2993.79   127.2 2993.48  133.75 2993.79   151.6 2995.15   159.7 2994.94
   167.8 2996.34     180 2996.59     184 2997.65   200.2 3004.58   204.3 3005.86
   224.6 3008.95   240.8 3010.58     253 3010.67   281.3 3013.14   297.4 3013.73
   318.9 3015.68   341.9 3016.88   349.9 3017.83     358 3017.93376.9829 3019.57
#Mann= 3 ,-1,0
       0      .1       0  122.08    .045       0  133.75      .1       0
Bank Sta=122.08,133.75
XS Rating Curve= 0 ,0
Exp/Cntr(USF)=0,0
Exp/Cntr=0.3,0.1

Type RM Length L Ch R = 1 ,2590    ,99.5,100.9,103.5
XS GIS Cut Line= 4
2354906.19346325650497.047834601 2354984.0669676650497.047834601
2355124.58731344650499.2230721532355290.34041487650418.739282743
#Sta/Elev= 30
       0 3020.53     6.1 3018.38    30.4 3011.54    46.7 3005.62    58.9 3002.59
    71.1  3000.7    87.3 2994.05    91.3 2993.27   103.4 2993.22   111.5 2990.85
   115.5 2990.79   139.8 2992.95   143.8 2991.99     164 2991.91     172 2991.04
  175.58 2991.89   184.1  2994.9   188.2 2995.48   204.3 2995.96   208.4 2996.79
   223.5 3002.83   237.8  3005.1   272.9 3006.69   299.2 3008.81   317.6  3009.7
   338.8  3012.6   360.7 3013.81   378.3 3015.69   387.1 3015.75402.6353 3017.59
#Mann= 3 ,-1,0
       0      .1       0     164    .045       0  175.58      .1       0
Bank Sta=164,175.58
XS Rating Curve= 0 ,0
Exp/Cntr(USF)=0,0
Exp/Cntr=0.3,0.1

Type RM Length L Ch R = 1 ,2489    ,150.9,140.8,128.5
XS GIS Cut Line= 6
2354900.94285997650552.734624318 2354974.8704399650561.012229793
2355038.80780632 650586.701350232355049.37721768650590.197324669
2355081.40933082650580.9999852532355314.96668647650564.931098796
#Sta/Elev= 30
       0 3023.76    31.4 3011.65    47.5 3004.97    55.6 3002.04    59.6 2999.94
    74.4 2994.27    84.4 2992.04    88.7 2991.52    97.3 2989.33   114.6  2989.7
  120.64 2989.11   127.5 2988.24  133.06 2989.28   144.7 2991.17   156.7 2992.53
   184.8 2994.21   196.8 2993.42   204.9 2994.43     245 2997.05     257 2998.39
   273.1 2998.94   289.1  3000.6   305.2 3000.85     313 3001.48   325.2 3005.51
   329.2 3006.17   337.3 3006.62   401.5 3014.61   413.5 3016.46420.3103 3016.98
#Mann= 3 ,-1,0
       0      .1       0  120.64    .045       0  133.06      .1       0
Bank Sta=120.64,133.06
XS Rating Curve= 0 ,0
Exp/Cntr(USF)=0,0
Exp/Cntr=0.3,0.1

Type RM Length L Ch R = 1 ,2348    ,137.8,145.3,150.3
XS GIS Cut Line= 6
2354928.09925498650731.9018503342355013.01385042650724.195112824
2355043.38885321650669.0816425682355064.08456992650639.512692391
2355104.75855873650588.6875950072355300.74818138650580.625864882
#Sta/Elev= 30
       0 3019.25    16.1  3014.4    28.4 3008.72    32.2 3006.36    44.3 3003.58
    52.3 3000.03    79.9 2992.55    88.7 2993.02    91.8 2992.71    97.8 2990.72
   106.4 2986.78   111.5 2986.15  123.06 2986.78     134 2987.98   182.3 2990.23
   192.4 2990.28   203.6 2991.64   214.5 2992.21   223.1  2993.8   238.5 2995.16
   248.8 2994.42   292.8 2998.04   304.8 2997.93   316.9  2999.8   348.9 3000.35
   364.9 3004.81   380.9 3007.57   388.9 3007.89   424.9 3012.86   445.5  3014.8
#Mann= 3 ,-1,0
       0      .1       0   106.4    .045       0  123.06      .1       0
Bank Sta=106.4,123.06
XS Rating Curve= 0 ,0
Exp/Cntr(USF)=0,0
Exp/Cntr=0.3,0.1

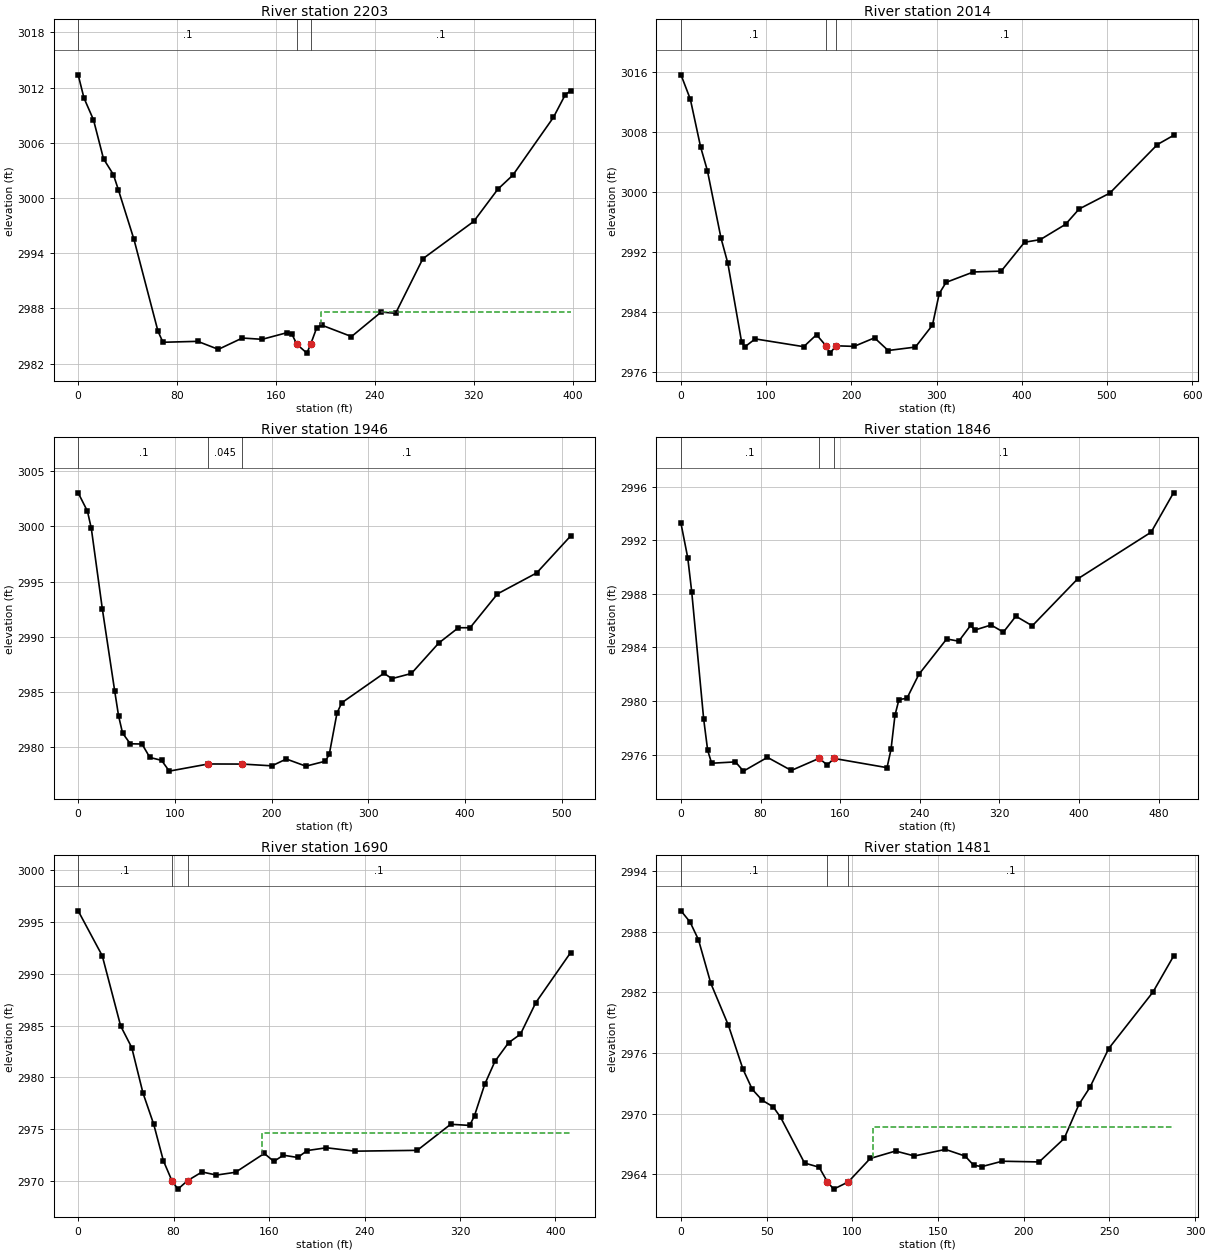
Type RM Length L Ch R = 1 ,2203    ,187.6,188.4,187.8
XS GIS Cut Line= 3
2354943.77482935650805.243805255  2355197.786907 650785.58109589
2355315.64994188650703.535270306
#Sta/Elev= 30
       0 3013.38     4.7 3010.86    12.4 3008.49    20.5 3004.26    28.5 3002.54
    32.5  3000.9    45.1 2995.52    64.6 2985.51    68.6 2984.33    96.7 2984.43
   113.4 2983.56   132.8 2984.79   148.8 2984.65   168.9 2985.37   172.9 2985.21
   176.9 2984.11     185 2983.15  188.02  2984.1     193 2985.92     197 2986.19
   221.1 2984.95   245.1 2987.61   256.8 2987.48   278.8  2993.4     320 2997.46
   339.5 3000.96   351.6 3002.48   384.4 3008.75   394.1 3011.24   398.4 3011.64
#Mann= 3 ,-1,0
       0      .1       0   176.9    .045       0  188.02      .1       0
#XS Ineff= 2 , 0
                          196.72         2987.65
Permanent Ineff=
       F       F
Bank Sta=176.9,188.02
XS Rating Curve= 0 ,0
Exp/Cntr(USF)=0,0
Exp/Cntr=0.3,0.1

Type RM Length L Ch R = 1 ,2014    ,70.5,68.1,67.9
XS GIS Cut Line= 2
2354913.19495506650968.0570830032355490.87298228650944.298728208
#Sta/Elev= 30
       0 3015.65      11 3012.38      23 3006.03      31 3002.85      47 2993.83
      55 2990.48    71.1    2980      75 2979.32    87.1 2980.38   144.1 2979.34
   159.1 2980.94   170.2 2979.46   175.1 2978.48181.95272979.461   203.2 2979.38
   227.2 2980.52   243.2 2978.83   275.2 2979.29   295.2 2982.22   303.2 2986.44
   311.2 2987.93   343.3 2989.32   375.9 2989.43   403.3 2993.29   421.8 2993.64
   451.4 2995.68   467.4 2997.73   503.4 2999.85   559.3 3006.34   578.2 3007.56
#Mann= 3 ,-1,0
       0      .1       0   170.2    .045       0181.9527      .1       0
Bank Sta=170.2,181.9527
XS Rating Curve= 0 ,0
Exp/Cntr(USF)=0,0
Exp/Cntr=0.3,0.1

Type RM Length L Ch R = 1 ,1946    ,101.1,100,96.1
XS GIS Cut Line= 3
2354930.68810455651027.8427692672355218.82056143651027.523142216
2355434.96128183651009.451704259
#Sta/Elev= 30
       0 3003.05     9.6 3001.38    13.6 2999.82      25 2992.51    37.8 2985.05
    41.8  2982.8    45.9 2981.25    53.9 2980.28      66 2980.26    74.1 2979.04
    86.2 2978.78    94.2  2977.8   134.6 2978.45   169.8 2978.44   200.3 2978.28
   215.2  2978.9   235.4 2978.25   255.5  2978.7   259.6 2979.32   267.6 2983.07
   272.5    2984   316.2 2986.68   324.3 2986.19   344.5 2986.66   372.8 2989.42
   393.1 2990.81   405.2 2990.81   433.5 2993.88     474 2995.78   509.2 2999.14
#Mann= 3 ,0,0
       0      .1       0   134.6    .045       0   169.8      .1       0
Bank Sta=134.6,169.8
XS Rating Curve= 0 ,0
Exp/Cntr(USF)=0,0
Exp/Cntr=0.3,0.1

Type RM Length L Ch R = 1 ,1846    ,154.3,156.5,156.3
XS GIS Cut Line= 3
2354953.42470229651110.1338828032355247.83271111651126.047829225
2355441.45239259651074.990584453
#Sta/Elev= 30
       0 2993.27     6.8  2990.7    10.8 2988.15    22.8 2978.65    26.8 2976.32
    30.8 2975.35    54.7 2975.45    62.8 2974.76    86.9 2975.79   110.9 2974.81
     139 2975.72     147 2975.21   153.7 2975.71   207.1 2975.02   211.1 2976.38
   215.1 2978.94   219.1 2980.11   227.1  2980.2   239.1 2981.99   267.1 2984.64
   279.2 2984.47   291.2 2985.66   295.2  2985.3   311.7 2985.68   324.1 2985.15
   336.6 2986.34   353.1 2985.62   398.6 2989.12   472.6 2992.62495.0762 2995.56
#Mann= 3 ,-1,0
       0      .1       0     139    .045       0   153.7      .1       0
Bank Sta=139,153.7
XS Rating Curve= 0 ,0
Exp/Cntr(USF)=0,0
Exp/Cntr=0.3,0.1

Type RM Length L Ch R = 1 ,1690    ,202.1,209,214.8
XS GIS Cut Line= 5
2354941.77386184651211.8008022442354993.90384139651243.508727948
2355040.12217377651251.0326425222355270.67641321651263.930781791
2355329.79288486651308.536846764
#Sta/Elev= 30
       0  2996.1    20.2 2991.75    35.6 2984.97    44.9 2982.88    54.3 2978.49
    63.3 2975.47    71.4 2971.94   78.55 2970.01    83.6 2969.19    91.7 2970.01
   103.8 2970.85   115.9 2970.55   131.9 2970.82     156 2972.64     164 2971.87
     172 2972.47     184 2972.25     192 2972.92   208.1 2973.19   232.1 2972.86
   284.2 2972.94   312.2 2975.46   328.2 2975.35   332.2  2976.3   340.7 2979.31
   349.3 2981.54   360.7 2983.34   370.7 2984.17   383.6 2987.23   412.8 2992.07
#Mann= 3 ,-1,0
       0      .1       0   78.55    .045       0    91.7      .1       0
#XS Ineff= 2 , 0
                          153.92         2974.61
Permanent Ineff=
       F       F
Bank Sta=78.55,91.7
XS Rating Curve= 0 ,0
Exp/Cntr(USF)=0,0
Exp/Cntr=0.3,0.1

Type RM Length L Ch R = 1 ,1481    ,191.8,192.4,190.4
XS GIS Cut Line= 6
2354852.70965223651341.5348233812354895.14021188651389.873435641
2354912.86436971651438.7491435932354941.86753706651469.363598024
2355020.82060376651520.9247844352355048.74957973651541.334420723
#Sta/Elev= 30
       0 2990.07     5.3 2988.96    10.2 2987.21    17.4  2982.9    27.7 2978.73
    36.2 2974.39    41.6 2972.41    47.4 2971.33    53.8 2970.68    58.1 2969.65
    72.1 2965.12    80.6 2964.71   85.49 2963.25    89.1 2962.54    97.6 2963.25
   110.4 2965.57   125.2 2966.31   136.2 2965.82   154.3 2966.47   165.8 2965.81
   170.8  2964.9   175.6 2964.77   187.4  2965.3     209 2965.23   223.6 2967.55
   232.3 2970.95   238.6  2972.6   249.6 2976.45   275.4 2982.03   287.4 2985.58
#Mann= 3 ,-1,0
       0      .1       0   85.49    .045       0    97.6      .1       0
#XS Ineff= 2 , 0
                           112.1         2968.66
Permanent Ineff=
       F       F
Bank Sta=85.49,97.6
XS Rating Curve= 0 ,0
Exp/Cntr(USF)=0,0
Exp/Cntr=0.3,0.1

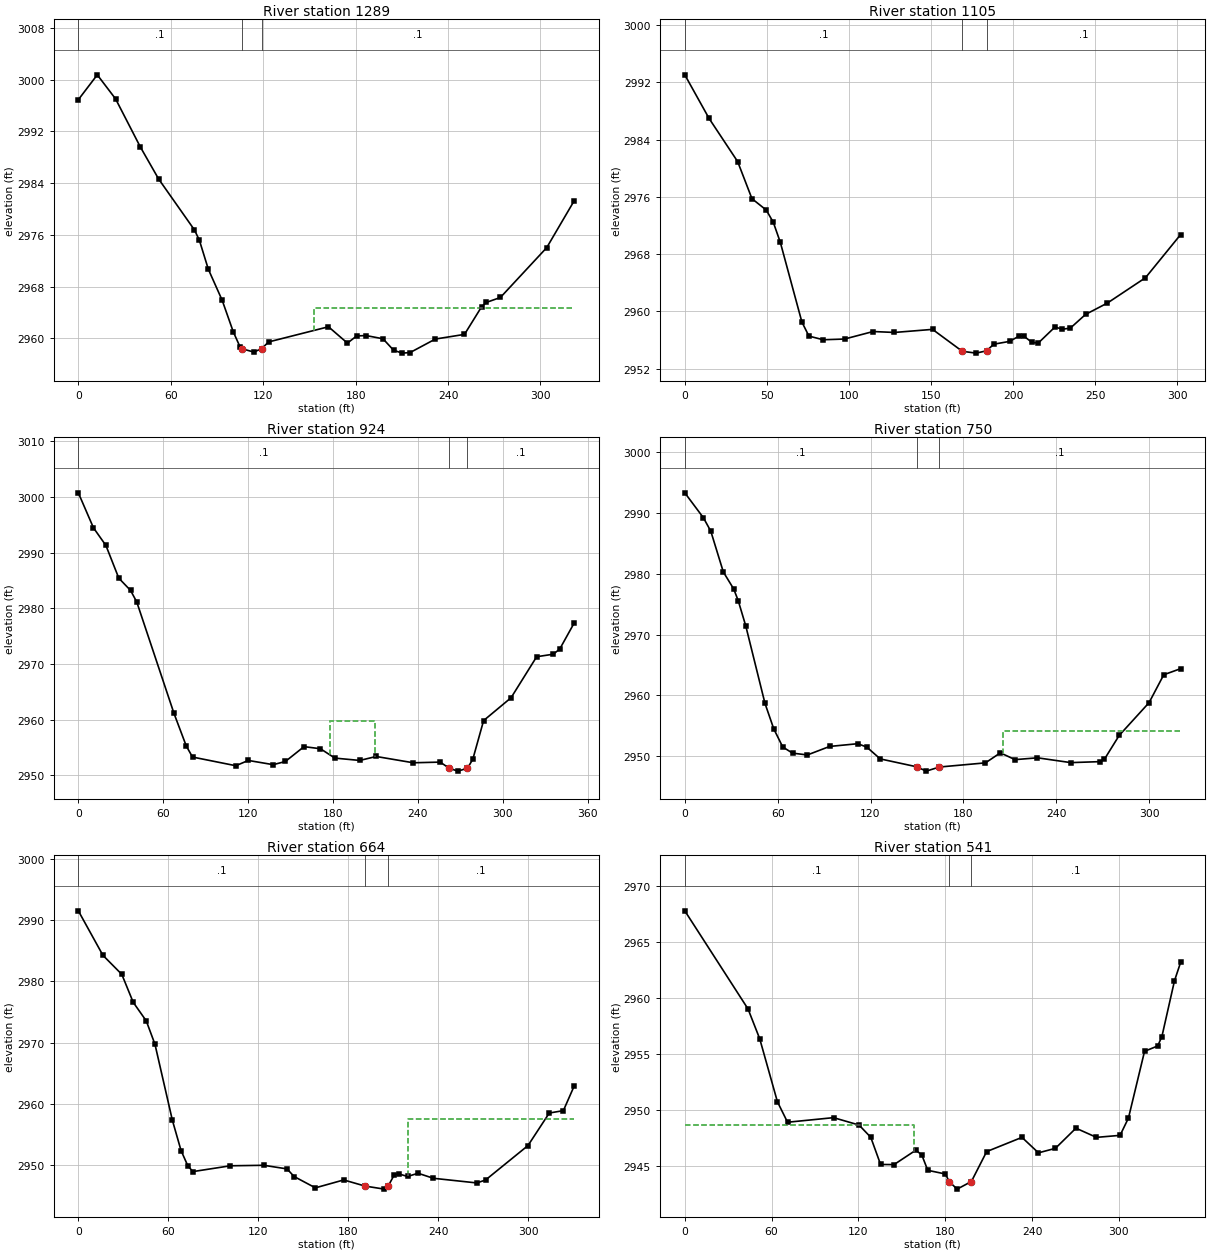
Type RM Length L Ch R = 1 ,1289    ,186,183.2,178.2
XS GIS Cut Line= 3
2354697.62801189651416.2122385932354692.37107036651405.126290672
2354823.42775836651685.655243962
#Sta/Elev= 30
       0 2996.92    12.3 3000.77    24.2 2997.04    40.2 2989.63    52.1 2984.66
    75.4 2976.76    78.6 2975.16    84.4 2970.68    93.4 2965.87   100.6 2960.99
     105 2958.66   106.3 2958.37   113.9 2957.87  118.99 2958.38   123.5 2959.43
   162.4 2961.78   174.7 2959.25   180.7 2960.36   186.8 2960.42   197.8 2959.92
   204.7 2958.14   210.3  2957.7   215.4 2957.79   231.8 2959.88   250.7  2960.6
   261.9 2964.91   264.9 2965.55     274 2966.31   304.1 2974.03   321.9 2981.27
#Mann= 3 ,-1,0
       0      .1       0   106.3    .045       0  118.99      .1       0
#XS Ineff= 2 , 0
                          152.74         2964.62
Permanent Ineff=
       F       F
Bank Sta=106.3,118.99
XS Rating Curve= 0 ,0
Exp/Cntr(USF)=0,0
Exp/Cntr=0.3,0.1

Type RM Length L Ch R = 1 ,1105    ,177,181.4,184.9
XS GIS Cut Line= 4
2354551.63656513651487.5086203672354608.66153981651622.777164963
2354699.50365064651677.1498152422354724.70073248651719.587005704
#Sta/Elev= 30
       0 2993.07    14.8 2986.97    32.2 2980.94    40.9 2975.76    49.6 2974.17
    53.9 2972.46    58.2 2969.64    71.3 2958.53    75.6 2956.55    84.3 2956.04
    97.3 2956.14   114.7 2957.19   127.7 2957.06   150.9 2957.49     1692954.429
   177.4 2954.17   183.82954.492   188.2 2955.42   197.8 2955.81   203.6 2956.55
   206.5 2956.55   211.5 2955.66   215.3 2955.58   225.5 2957.83   229.8 2957.51
   234.8 2957.66   244.1 2959.58   257.4 2961.17   280.6 2964.71     302 2970.74
#Mann= 3 ,-1,0
       0      .1       0     169    .045       0   183.8      .1       0
Bank Sta=169,183.8
XS Rating Curve= 0 ,0
Exp/Cntr(USF)=0,0
Exp/Cntr=0.3,0.1

Type RM Length L Ch R = 1 ,924     ,174.3,173.9,171.2
XS GIS Cut Line= 3
2354416.17412008651535.4098038252354545.07708611651825.978573072
2354561.72705255651853.907549044
#Sta/Elev= 30
       0 3000.77    10.7 2994.48    19.5 2991.31    28.6 2985.44    36.9 2983.24
    41.3 2981.16    67.6 2961.15    76.3 2955.28    80.7 2953.31   111.3 2951.75
   120.1  2952.7   137.7 2951.94   146.3 2952.51   159.5 2955.18   171.1  2954.8
   181.3 2953.12   198.9  2952.7   210.5 2953.41   236.7 2952.28   255.7  2952.4
     262 2951.32   268.1 2950.78     2752951.287   278.8 2952.94   286.4 2959.86
   305.8 2963.96   323.9 2971.33   335.6 2971.78   340.2 2972.71 350.393 2977.38
#Mann= 3 ,-1,0
       0      .1       0     262    .045       0     275      .1       0
#XS Ineff= 1 ,-1
  177.78  209.84 2959.76
Permanent Ineff=
       F
Bank Sta=262,275
XS Rating Curve= 0 ,0
Exp/Cntr(USF)=0,0
Exp/Cntr=0.3,0.1

Type RM Length L Ch R = 1 ,750     ,83.9,86.2,84.7
XS GIS Cut Line= 2
2354278.43451074651607.1678002282354455.36629437651874.245505646
#Sta/Elev= 30
       0  2993.3      12 2989.21    16.8 2986.99    24.9 2980.28    31.6 2977.49
    34.5 2975.58    39.4 2971.41    51.8 2958.68    57.5 2954.47    63.3  2951.5
    69.6 2950.49    79.2 2950.19    93.6 2951.59   111.8 2952.04   117.6 2951.48
   126.3 2949.54   149.9 2948.24     156 2947.53164.50272948.204   194.3 2948.89
   203.9 2950.54   213.4 2949.42   227.9 2949.72   249.4 2948.93   268.2 2949.09
   271.1 2949.46   280.7  2953.4     300 2958.79   309.5 2963.38   320.4 2964.38
#Mann= 3 ,-1,0
       0      .1       0   149.9    .045       0164.5027      .1       0
#XS Ineff= 2 , 0
                          205.37          2954.1
Permanent Ineff=
       F       F
Bank Sta=149.9,164.5027
XS Rating Curve= 0 ,0
Exp/Cntr(USF)=0,0
Exp/Cntr=0.3,0.1

Type RM Length L Ch R = 1 ,664     ,125.6,123,113.4
XS GIS Cut Line= 2
2354211.15506719 651637.525395762354396.44802677651911.996592752
#Sta/Elev= 30
       0 2991.49    16.4 2984.23      29 2981.12    36.6 2976.56    45.3 2973.53
    51.1 2969.72    62.7 2957.33    68.5 2952.37      73 2949.89    76.4 2948.93
   101.4 2949.88   123.7 2949.96   139.2 2949.37   143.9 2948.13   158.1 2946.28
     177 2947.57   191.2 2946.57   204.1 2946.07  206.64 2946.56   210.7 2948.39
   213.6 2948.56   219.6 2948.14   226.6 2948.66   236.8 2947.84   265.8 2947.08
   271.6 2947.56   299.9 2953.18   314.1 2958.49   323.5 2958.88   330.7 2962.89
#Mann= 3 ,-1,0
       0      .1       0   191.2    .045       0  206.64      .1       0
#XS Ineff= 2 , 0
                          219.81         2957.56
Permanent Ineff=
       F       F
Bank Sta=191.2,206.64
XS Rating Curve= 0 ,0
Exp/Cntr(USF)=0,0
Exp/Cntr=0.3,0.1

Type RM Length L Ch R = 1 ,541     ,60.6,60.2,60.7
XS GIS Cut Line= 4
2354154.94318136651737.8970260852354173.44314408651865.009673137
2354280.26550944651885.2999548262354369.18468508651941.993388958
#Sta/Elev= 30
       0 2967.76    43.7    2959    51.8 2956.33      64 2950.72      71 2948.89
   102.8  2949.3   120.4 2948.64   128.5 2947.55   135.3 2945.12   144.6 2945.11
   159.7  2946.4   163.8 2945.96   167.9  2944.6   180.1 2944.27  182.74 2943.59
   188.2 2942.92  198.05  2943.6   208.6 2946.27     233 2947.54   244.4 2946.16
   256.1 2946.56   270.3 2948.36   284.5 2947.54   300.8 2947.72   306.6 2949.27
   317.7 2955.22   326.8  2955.7   329.7 2956.54   338.4 2961.52342.6392 2963.16
#Mann= 3 ,-1,0
       0      .1       0  182.74    .045       0  198.05      .1       0
#XS Ineff= 2 , 0
          158.08 2948.67
Permanent Ineff=
       F       F
Bank Sta=182.74,198.05
XS Rating Curve= 0 ,0
Exp/Cntr(USF)=0,0
Exp/Cntr=0.3,0.1

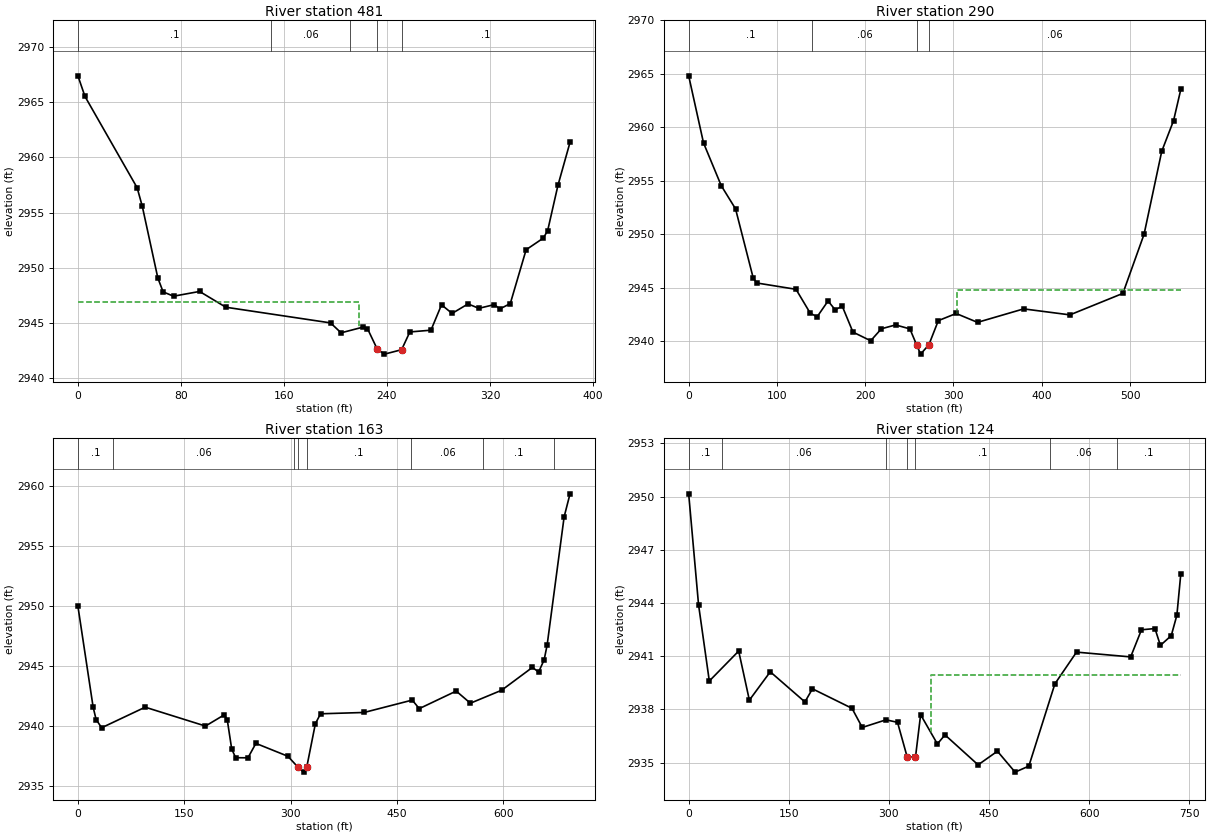
Type RM Length L Ch R = 1 ,481     ,180.8,190.8,200.1
XS GIS Cut Line= 4
2354122.97776364651743.7205482242354149.09578814651918.368941414
2354163.73412107651921.8267414972354349.39682934651964.927013059
#Sta/Elev= 30
       0 2967.39     5.5 2965.52      46 2957.25      50 2955.57    62.1 2949.06
    66.2 2947.81    74.3 2947.42    94.5 2947.85   114.9 2946.42   196.2    2945
   204.4  2944.1   221.5 2944.62   224.9 2944.48  232.61 2942.59   238.1 2942.17
   251.4 2942.57   257.8 2944.18   274.2 2944.34   282.4 2946.64   290.6 2945.86
     303 2946.72   311.4 2946.32   323.5 2946.66   327.6 2946.26   335.8 2946.75
   348.1 2951.63   361.4 2952.68   364.8 2953.35   372.8 2957.46   382.2 2961.37
#Mann= 5 ,-1,0
       0      .1       0     150     .06       0  211.63      .1       0
  232.61    .045       0   251.4      .1       0
#XS Ineff= 2 , 0
          218.65  2946.9
Permanent Ineff=
       F       F
Bank Sta=232.61,251.4
XS Rating Curve= 0 ,0
Exp/Cntr(USF)=0,0
Exp/Cntr=0.3,0.1

Type RM Length L Ch R = 1 ,290     ,130.7,126.3,123.3
XS GIS Cut Line= 3
 2354066.5163634651744.5132292992354108.35687183652081.966025531
 2354325.7456004 652075.59899164
#Sta/Elev= 30
       0  2964.8    16.8 2958.53    36.9 2954.53    53.1 2952.36    73.2 2945.87
    77.3 2945.43   121.6 2944.84   137.7 2942.61   145.5 2942.27   157.9 2943.75
   165.9 2942.93     174 2943.26   186.1 2940.84   206.2 2940.03   218.3 2941.15
   234.4 2941.51   250.6 2941.14  258.16 2939.66   262.7 2938.78  272.08 2939.65
   282.8 2941.91     303 2942.58   327.2 2941.75   379.5 2943.01   431.9 2942.45
   491.9 2944.46   515.9 2949.99   535.9 2957.74   549.3 2960.61557.5187 2963.53
#Mann= 4 ,-1,0
       0      .1       0     140     .06       0  258.16    .045       0
  272.08     .06       0
#XS Ineff= 2 , 0
                          303.83         2944.76
Permanent Ineff=
       F       F
Bank Sta=258.16,272.08
XS Rating Curve= 0 ,0
Exp/Cntr(USF)=0,0
Exp/Cntr=0.3,0.1

Type RM Length L Ch R = 1 ,163     ,38,39.1,39.6
XS GIS Cut Line= 6
2353813.48042743651743.7169588122353810.25785328 651818.91035566
2353898.87864242651912.9021017212353996.09296263652007.968039165
2354090.62180438652099.2743067672354312.44232509652086.921105856
#Sta/Elev= 30
       0 2949.99    21.5 2941.59    25.7 2940.56    33.5 2939.88    94.9 2941.59
   179.9 2940.02   206.3 2940.95   210.6 2940.55   216.9 2938.11   222.5 2937.39
   239.8 2937.38     251 2938.58   296.1 2937.51   310.2 2936.61   318.2 2936.19
  322.71  2936.6   334.9 2940.22   342.2 2941.04   403.6 2941.15   471.5 2942.18
   481.4 2941.47   533.5 2942.93   553.5 2941.92   597.6    2943     641  2944.9
   649.7 2944.51   657.5 2945.53   661.7 2946.75   685.7 2957.42694.0052 2959.33
#Mann= 8 ,-1,0
       0      .1       0      50     .06       0  304.44      .1       0
   310.2    .045       0  322.71      .1       0  470.42     .06       0
  571.84      .1       0  671.84     .06       0
Bank Sta=310.2,322.71
XS Rating Curve= 0 ,0
Exp/Cntr(USF)=0,0
Exp/Cntr=0.3,0.1

Type RM Length L Ch R = 1 ,124     ,,,
XS GIS Cut Line= 6
2353801.93287006651738.3460018942353798.17320021651846.302235941
2353873.90369275651922.569824173 2353961.9873862652031.600249603
2354075.31457717652165.8741725472354278.33674866652132.574239657
#Sta/Elev= 30
       0 2950.16    14.8  2943.9    30.9  2939.6    74.9 2941.29    90.9 2938.52
   122.2 2940.12   174.1 2938.42   185.4 2939.16   244.6 2938.06     260 2936.98
   295.5 2937.41   312.8 2937.27   327.3 2935.31  339.72 2935.31   347.4  2937.7
   372.5 2936.05   383.9 2936.56   433.5 2934.87   462.4 2935.64   488.9 2934.46
   509.5  2934.8   548.5 2939.44   580.9 2941.23     662 2940.96   678.2 2942.49
   698.4 2942.56   706.5 2941.61   722.8 2942.16   731.2 2943.31   737.1 2945.65
#Mann= 7 ,-1,0
       0      .1       0      50     .06       0   295.5      .1       0
   327.3    .045       0  339.72      .1       0  541.37     .06       0
  641.37      .1       0
#XS Ineff= 2 , 0
                          362.84         2939.95
Permanent Ineff=
       F       F
Bank Sta=327.3,339.72
XS Rating Curve= 0 ,0
Exp/Cntr(USF)=0,0
Exp/Cntr=0.3,0.1
LCMann Table=0

Chan Stop Cuts=-1
Use User Specified Reach Order=0
Composite Channel Slope=5